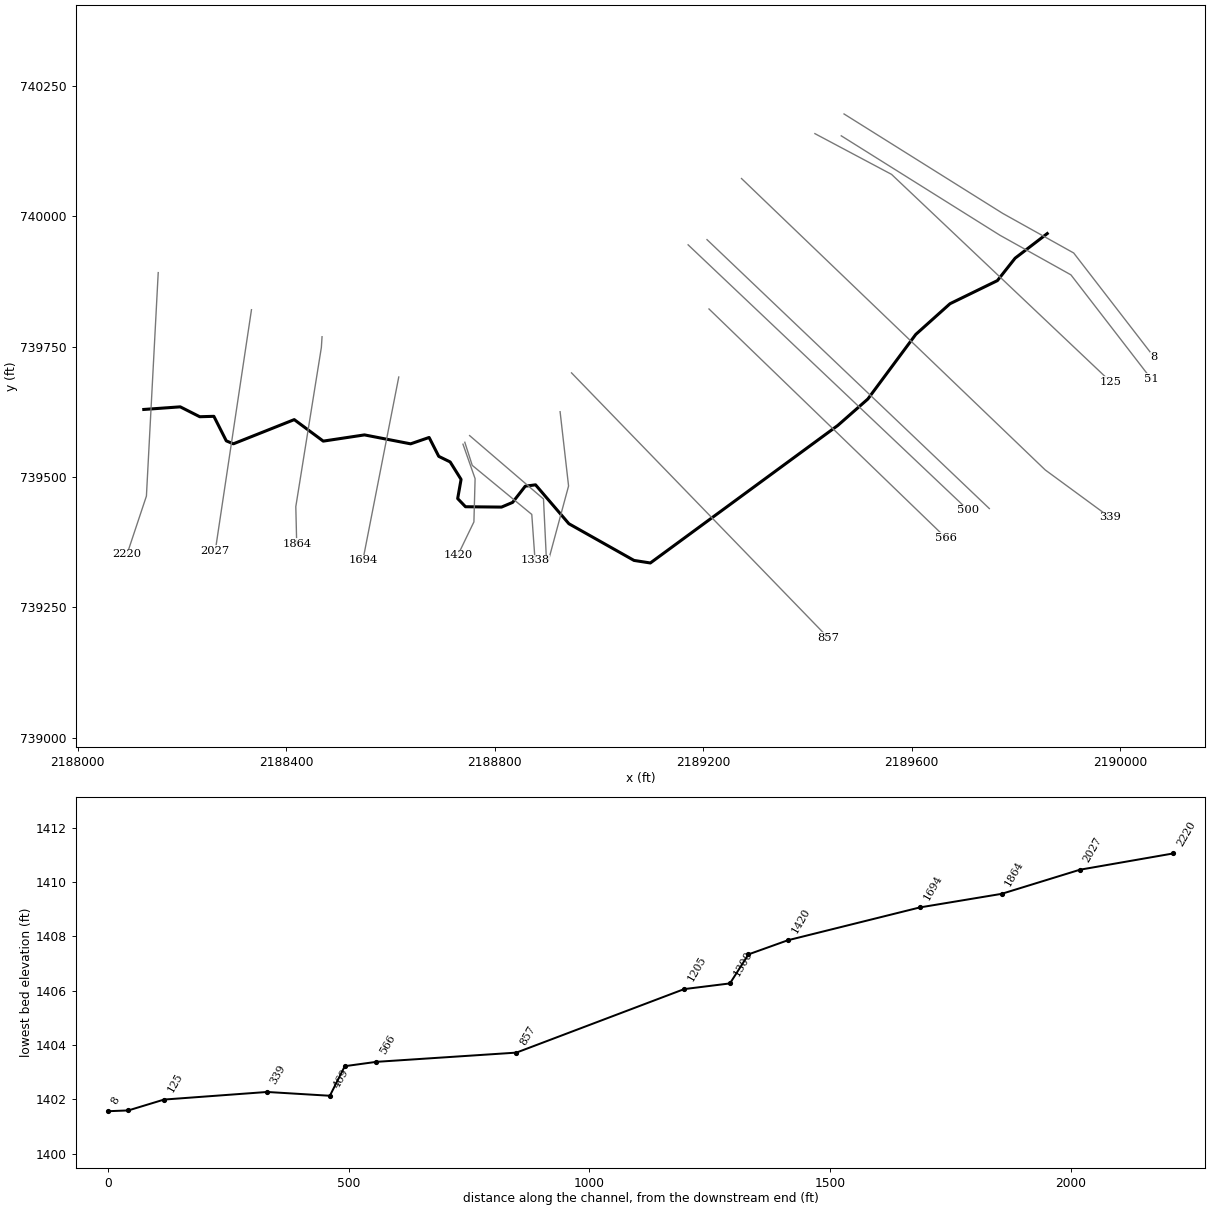
--- THREELKRN.prj (project) ---

Proj Title=THREELKRN
Current Plan=p01
Default Exp/Contr=0.3,0.1
English Units
Geom File=g01
Flow File=f01
Plan File=p01
Y Axis Title=Elevation
X Axis Title(PF)=Main Channel Distance
X Axis Title(XS)=Station
BEGIN DESCRIPTION:
---------- MODELED AS PART OF WVEMD CTP PROGRAM, 2023----------
Stream Name: Three Lick Run
Flood Zone:  AFH
Upshur County, WV
HEC-RAS Version: RAS 6.3
Vertical Datum: NAVD88
Projection: NAD 1983 StatePlane West Virginia S FIPS 4702 (US Feet)
Terrain: 1-meter LIDAR (FEMA Region III 3DEP collected 2016-2018)
Land Use: 2019 NLCD
Hydrologic Method:
WV SIR2010-5033 regression equations
Additional Model Notes:
None
END DESCRIPTION:
DSS Export Rating Curves= 0
DSS Export Rating Curve Sorted= 0
DSS Export Volume Flow Curves= 0
DXF OffsetX= 0
DXF OffsetY= 0
DXF ScaleX= 1
DXF ScaleY= 10

--- THREELKRN.p01 (plan) ---

Plan Title=Floodplain
Program Version=6.30
Short Identifier=Floodplain
Geom File=g01
Flow File=f01
Subcritical Flow
K Sum by GR= 0
Std Step Tol= 0.01
Critical Tol= 0.01
Num of Std Step Trials= 20
Max Error Tol= 0.3
Flow Tol Ratio= 0.001
Split Flow NTrial= 30
Split Flow Tol= 0.02
Split Flow Ratio= 0.02
Log Output Level= 0
Friction Slope Method= 1
Unsteady Friction Slope Method= 2
Unsteady Bridges Friction Slope Method= 1
Parabolic Critical Depth
Global Vel Dist= 0 , 0 , 0
Global Log Level= 0
CheckData=True
Encroach Param=-1 ,0,0, 0
Computation Interval=1MIN
Output Interval=1HOUR
Instantaneous Interval=1HOUR
Mapping Interval=1HOUR
Computation Time Step Use Courant=        0
Computation Time Step Use Time Series=    0
Computation Time Step Count To Double=0
Computation Time Step Max Doubling=0
Computation Time Step Max Halving=0
Computation Time Step Residence Courant=0
Run HTab= 0
Run UNet= 0
Run Sediment= 0
Run PostProcess= 0
Run WQNet= 0
Run RASMapper=-1
UNET Theta= 1
UNET Theta Warmup= 1
UNET ZTol= 0.02
UNET ZSATol= 0.02
UNET MxIter= 20
UNET Max Iter WO Improvement= 0
UNET MaxInSteps= 0
UNET DtIC= 0
UNET DtMin= 0
UNET MaxCRTS= 20
UNET WFStab= 2
UNET SFStab= 1
UNET WFX= 1
UNET SFX= 1
UNET Gravity=32.17405
UNET 1D Methodology=Finite Difference
UNET DSS MLevel= 4
UNET Pardiso=0
UNET DZMax Abort= 100
UNET Use Existing IB Tables=-1
UNET Froude Reduction=False
UNET Froude Limit= 0.8
UNET Froude Power= 4
UNET D1 Cores= 0
UNET WindReference=Eulerian
UNET WindDragFormulation=Hsu (1988)
UNET D2 Coriolis=0
UNET D2 Cores= 0
UNET D2 Theta= 1
UNET D2 Theta Warmup= 1
UNET D2 Z Tol= 0.01
UNET D2 Volume Tol= 0.01
UNET D2 Max Iterations= 20
UNET D2 Equation= 0
UNET D2 RampUpFraction=0.1
UNET D2 TimeSlices= 1
UNET D2 Turbulence Formulation=None
UNET D2 Eddy Viscosity=0.3
UNET D2 Transverse Eddy Viscosity=0.1
UNET D2 Smagorinsky Mixing=0.05
UNET D2 BCVolumeCheck=0
UNET D2 Cores=0
UNET D2 SolverType=PARDISO (Direct)
UNET D2 Minimum Iterations= 3
UNET D2 Maximum Iterations= 30
UNET D2 Restart Number= 10
UNET D2 Relaxation Coeff=1.3
UNET D2 SOR Precondition Iterations= 10
UNET D2 ILUT Maximum Fill= 8
UNET D2 ILUT Tolerance=1E-08
UNET D2 Convergence Tolerance=0.00001
UNET D1D2 MaxIter= 0
UNET D1D2 ZTol=0.01
UNET D1D2 QTol=0.1
UNET D1D2 MinQTol=1
Write IC File= 0
Write IC File at Fixed DateTime=0
Write IC File at Sim End=0
Echo Input=False
Echo Parameters=False
Echo Output=False
Write Detailed= 0
HDF Write Warmup=0
HDF Write Time Slices=0
HDF Flush=0
HDF Compression= 1
HDF Chunk Size= 1
HDF Spatial Parts= 1
HDF Use Max Rows=0
HDF Fixed Rows= 1
Calibration Method= 0
Calibration Iterations= 20
Calibration Max Change=0.05
Calibration Tolerance=0.2
Calibration Maximum=1.5
Calibration Minimum=0.5
Calibration Optimization Method= 1
WQ AD Non Conservative
WQ ULTIMATE=-1
WQ Max Comp Step=1HOUR
WQ Output Interval=15MIN
WQ Output Selected Increments= 0
WQ Output face flow=0
WQ Output face velocity=0
WQ Output face area=0
WQ Output face dispersion=0
WQ Output cell volume=0
WQ Output cell surface area=0
WQ Output cell continuity=0
WQ Output cumulative cell continuity=0
WQ Output face conc=0
WQ Output face dconc_dx=0
WQ Output face courant=0
WQ Output face peclet=0
WQ Output face adv mass=0
WQ Output face disp mass=0
WQ Output cell mass=0
WQ Output cell source sink temp=0
WQ Output nsm pathways=0
WQ Output nsm derived pathways=0
WQ Create Restart=0
WQ Fixed Restart=0
WQ System Summary=0
WQ Write To DSS=0
Sorting and Armoring Iterations= 10
XS Update Threshold= 0.02
Bed Roughness Predictor= 0
Hydraulics Update Threshold= 0.02
Energy Slope Method= 1
Volume Change Method= 1
Sediment Retention Method= 0
Sediment TS Multiplier= 1
Warm Up Method= 0
XS Weighting Method= 0
Number of US Weighted Cross Sections= 1
Number of DS Weighted Cross Sections= 1
Upstream XS Weight=0
Main XS Weight=1
Downstream XS Weight=0
Number of DS XS's Weighted with US Boundary= 1
Upstream Boundary Weight= 1
Weight of XSs Associated with US Boundary= 0
Number of US XS's Weighted with DS Boundary= 1
Downstream Boundary Weight= 0.5
Weight of XSs Associated with DS Boundary= 0.5
Percentile Method= 0
Sediment Output Level= 3
Mass or Volume Output= 0
Output Increment Type= 1
Profile and TS Output Increment= 1
Transport Output Increment 1
XS Output Flag= 0
XS Output Increment= 10
Read HDF5 Sediment Hotstart= 0
Sediment Hotstart Type= 0
Write Gradation File= 0
Read Gradation Hotstart= 0
Write HDF5 File= 1
Write Binary Output= 1
Write DSS Sediment File= 0
DSS Sediment Output Type= 1
SV Curve= 0
Specific Gage Flag= 0
Subcell Erosion Methods= 0
Subcell Deposition Methods= 0
Advection Scheme= 1
Matrix Solver= 0
Implicit Weighting Factor= 1
Maximum Outer Loop Convergence Iterations= 5
Convergence Maximum Absolute= 0.001
Convergence RMSE= 0.0001
Grain Fractions Max Abs Error= 0.001
Max Subgrid Regions= 1
Max Subgrid Length Scale= 3.402823E+38
Initial Layer Thickness= 3.402823E+38
Min Layer Thickness= 3.402823E+38
Max Layer Thickness= 3.402823E+38
Number of Layers= 5

--- THREELKRN.f01 (steady flow) ---

Flow Title=Flows
Program Version=6.31
Number of Profiles= 1
Profile Names=01pct
River Rch & RM=THREELKRN,Main            ,2220
     318
Boundary for River Rch & Prof#=THREELKRN,Main            , 1
Up Type= 0
Dn Type= 3
Dn Slope=0.00087
DSS Import GetInterval= 0
DSS Import GetPeak= 0
DSS Import FillOption= 0

--- THREELKRN.g01 (geometry) ---

Geom Title=Geometry
Program Version=6.31

River Reach=THREELKRN       ,Main
Reach XY= 30
2188127.01469778739629.4139565362188196.95107401739634.446278811
2188234.37090631739615.4782948532188261.46802625 739616.25249828
2188285.28993999739569.1763484692188298.83540314739563.504185773
2188415.62120027739609.9338697712188471.27054142 739568.69756371
 2188550.3347187739580.6156388592188638.83042173 739563.47355841
2188674.36635903739575.7021015372188692.81623626739539.447313696
2188714.68369334 739528.780261462188735.63683166739495.255240148
2188729.12615494739458.4853907432188744.11082356739442.823448968
2188813.19268565739442.1461758112188834.47862067739451.155360927
 2188858.7498981739482.2783386862188878.49208548739484.833209995
2188942.41523568739410.242427444 2189067.3452092739339.855892769
2189098.70044798739334.9526043992189458.25967087739598.771160867
2189515.85296747 739649.422357532189607.77291756739773.324423554
2189673.49189982739832.2560954792189764.37104463739876.574521762
2189798.36140253739919.5899145922189860.01118158739966.812542212

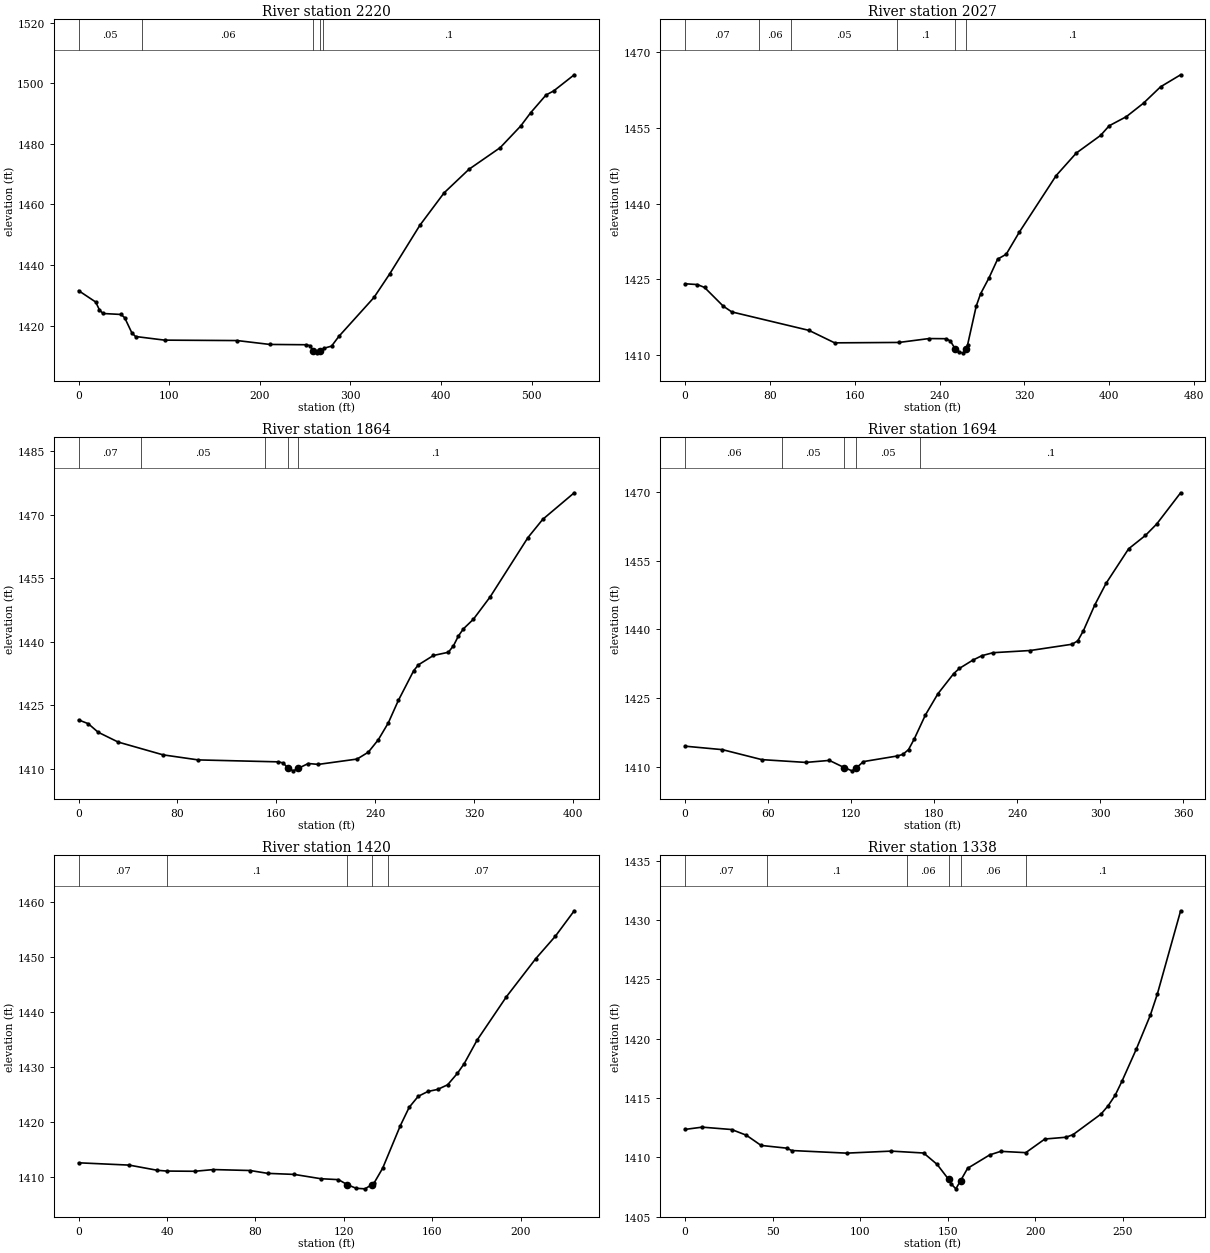
Type RM Length L Ch R = 1 ,2220    ,356.7,193.9,356.7
XS GIS Cut Line= 3
2188154.71841465739891.9292784182188132.07136418739463.252965828
2188094.86549554739351.635359908
#Sta/Elev= 30
       0 1431.57    18.8 1427.83    22.8 1425.33    26.8 1424.04    46.8 1423.72
    50.8 1422.65    58.8 1417.61    62.8 1416.45    94.9 1415.25     175 1415.11
     211 1413.83   251.1 1413.73   255.1 1413.44259.11721411.747   263.1 1411.06
266.61721411.683   271.1  1412.6   279.1 1413.28   287.2  1416.5   325.9 1429.32
   343.2 1437.07   376.6 1453.16   403.3 1463.84   430.8 1471.63   465.2 1478.75
   487.8 1485.88   498.9  1490.3   515.8 1496.13   524.2 1497.46   546.9 1502.79
#Mann= 5 ,-1,0
       0     .05       0      70     .06       0259.1172    .045       0
266.6172     .06       0     270      .1       0
Bank Sta=259.1172,266.6172
XS Rating Curve= 0 ,0
Exp/Cntr(USF)=0,0
Exp/Cntr=0.3,0.1

Type RM Length L Ch R = 1 ,2027    ,162.6,162.8,162.4
XS GIS Cut Line= 2
2188333.58238961739820.7412073592188264.18411413739358.478118124
#Sta/Elev= 30
       0 1424.15    11.7 1423.99    18.4 1423.42      36 1419.72    44.1 1418.57
   116.9 1414.91   141.1 1412.44   201.8 1412.52   230.1 1413.29   246.3 1413.26
   250.3 1412.79   254.61411.298   258.4 1410.56   262.5 1410.46  264.53 1411.25
   266.5 1412.07   274.6 1419.71   278.7 1422.15   286.7 1425.33   294.8 1429.03
   302.9    1430   315.1 1434.33     350 1445.59     369 1450.06   391.9 1453.55
     400 1455.46   416.2 1457.27   432.4 1459.95   448.5 1463.19   467.4 1465.57
#Mann= 6 ,-1,0
       0     .07       0      70     .06       0     100     .05       0
     200      .1       0   254.6    .045       0  264.53      .1       0
Bank Sta=254.6,264.53
XS Rating Curve= 0 ,0
Exp/Cntr(USF)=0,0
Exp/Cntr=0.3,0.1

Type RM Length L Ch R = 1 ,1864    ,168.2,169.6,167.5
XS GIS Cut Line= 4
 2188468.9586995739768.951932673 2188467.6263408739748.221507267
2188418.62437253739443.0338101922188420.34373984739371.680066932
#Sta/Elev= 30
       0 1421.59     7.8 1420.69    15.8 1418.68      32 1416.36    68.4 1413.34
    96.8 1412.15   161.6 1411.69   165.6 1411.43169.37341410.211   173.8 1409.57
177.77341410.156   185.9  1411.3     194 1411.09   225.4 1412.35   234.5 1413.97
   242.6 1416.91   250.7 1420.89   258.8 1426.17   271.2 1433.18     275 1434.57
   287.2 1436.79   299.3 1437.55   303.4 1439.06   307.4 1441.37   311.5 1443.08
   319.6 1445.35   333.2 1450.64   363.7  1464.6   375.7 1468.91   401.2 1475.18
#Mann= 5 ,-1,0
       0     .07       0   50.77     .05       0  150.77      .1       0
169.3734    .045       0177.7734      .1       0
Bank Sta=169.3734,177.7734
XS Rating Curve= 0 ,0
Exp/Cntr(USF)=0,0
Exp/Cntr=0.3,0.1

Type RM Length L Ch R = 1 ,1694    ,270.3,274.1,273.5
XS GIS Cut Line= 2
2188616.10656836739691.6728360752188547.29641386739340.211739222
#Sta/Elev= 30
       0 1414.46      27  1413.7    55.5 1411.52    87.3 1410.91   104.3 1411.35
   115.21409.755   120.7 1409.07   123.61409.664   128.9 1411.09   153.4 1412.32
   157.4 1412.66   161.5 1413.72   165.6 1416.02   173.7 1421.29   182.7 1425.91
   194.1 1430.31   198.2 1431.45   207.8 1433.24   214.5 1434.24   222.6 1434.89
   249.5 1435.37   279.7 1436.74   283.8 1437.49   287.9 1439.73     296 1445.28
   304.2 1450.04   320.5 1457.59   332.7 1460.53   340.8 1463.01   358.1 1469.84
#Mann= 5 ,-1,0
       0     .06       0      70     .05       0   115.2    .045       0
   123.6     .05       0     170      .1       0
Bank Sta=115.2,123.6
XS Rating Curve= 0 ,0
Exp/Cntr(USF)=0,0
Exp/Cntr=0.3,0.1

Type RM Length L Ch R = 1 ,1420    ,73.8,81.7,90.6
XS GIS Cut Line= 4
2188739.29131308739562.7690058412188762.53202503739496.692471869
2188760.25352386739413.7550292282188729.26590792739349.501296192
#Sta/Elev= 30
       0 1412.59    22.9 1412.17    35.6 1411.23    39.8 1411.09    52.6 1411.05
      61 1411.36    77.6 1411.19    85.6 1410.67    97.6 1410.48   109.6  1409.7
   117.6 1409.53   121.6 1408.62   125.6 1407.96   129.6 1407.86   132.7 1408.62
   133.6 1408.84   137.6 1411.61   145.6 1419.34   149.6 1422.67   153.7 1424.67
   158.1 1425.55   162.5 1425.92     167 1426.76   171.4 1428.83   174.5  1430.6
   180.3 1434.85   193.6 1442.75   206.9 1449.68   215.8 1453.77   224.3 1458.37
#Mann= 5 ,-1,0
       0     .07       0      40      .1       0   121.6    .045       0
   132.7      .1       0  140.04     .07       0
Bank Sta=121.6,132.7
XS Rating Curve= 0 ,0
Exp/Cntr(USF)=0,0
Exp/Cntr=0.3,0.1

Type RM Length L Ch R = 1 ,1338    ,38.5,38.5,39.7
XS GIS Cut Line= 4
2188742.78980733739566.4819799492188757.06362222739522.211684989
2188871.26455967739428.0732264382188877.51559169739339.864219038
#Sta/Elev= 30
       0 1412.35     9.8 1412.54    26.6 1412.34      35 1411.86    43.4    1411
      58 1410.77    60.9 1410.57    92.2 1410.35   117.7 1410.52   136.2 1410.36
   143.9  1409.4   150.4 1408.15   151.8 1407.77   154.6 1407.34   157.31408.032
   161.3 1409.07   173.9  1410.2   180.2  1410.5   194.5 1410.39   205.4 1411.54
   217.5 1411.69   221.5 1411.91   237.5 1413.65   241.5 1414.34   245.5 1415.22
   249.5 1416.44   257.6 1419.12   265.6 1421.98   269.6 1423.76   282.9 1430.78
#Mann= 6 ,-1,0
       0     .07       0   46.51      .1       0  126.51     .06       0
   150.4    .045       0   157.3     .06       0  194.51      .1       0
Bank Sta=150.4,157.3
XS Rating Curve= 0 ,0
Exp/Cntr(USF)=0,0
Exp/Cntr=0.3,0.1

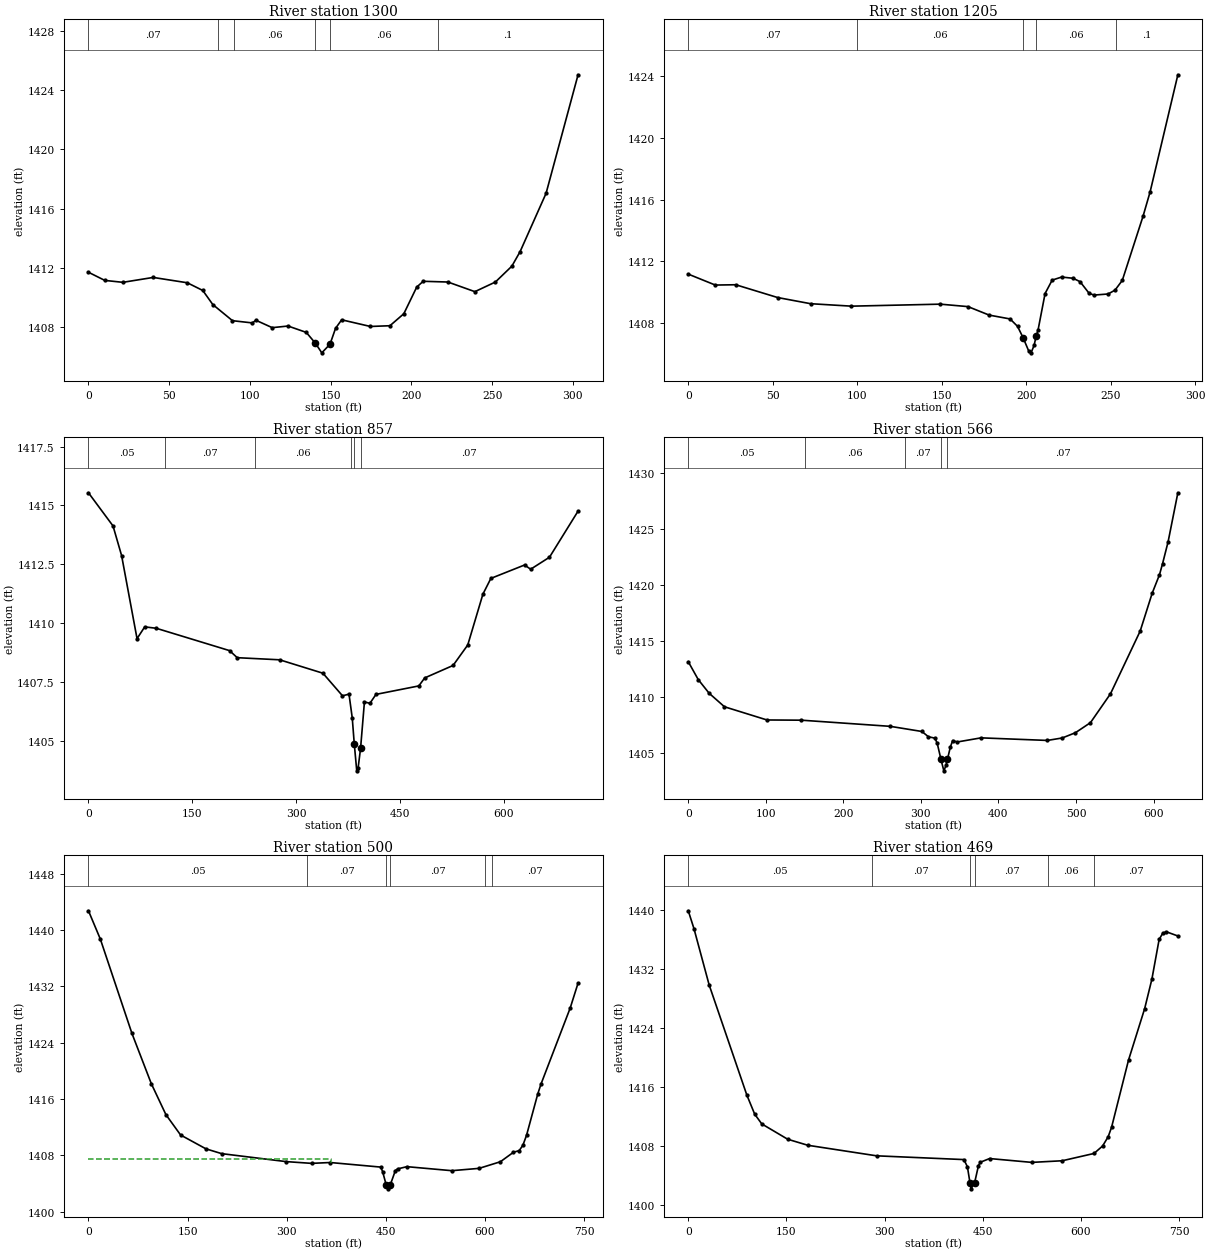
Type RM Length L Ch R = 1 ,1300    ,103.8,95.1,84.8
XS GIS Cut Line= 3
2188752.02091469739579.2889554412188893.71097382739457.741110598
2188899.33690263739341.402459107
#Sta/Elev= 30
       0 1411.71    10.1 1411.16    21.3 1411.03    40.1 1411.36    61.2    1411
    70.8 1410.48      77 1409.53    89.2 1408.44   101.5 1408.29   103.7 1408.47
   113.8 1407.97   123.6 1408.08   134.9 1407.65   140.6 1406.91   144.5 1406.27
   149.61406.855     153 1407.92   156.8  1408.5   174.6 1408.05   186.7  1408.1
   195.3 1408.91   203.3 1410.71   207.3  1411.1   222.6 1411.05   239.3  1410.4
     252 1411.05   262.2 1412.12   267.3  1413.1   283.4 1417.04   303.2 1425.04
#Mann= 6 ,-1,0
       0     .07       0      80      .1       0      90     .06       0
   140.6    .045       0   149.6     .06       0  216.68      .1       0
Bank Sta=140.6,149.6
XS Rating Curve= 0 ,0
Exp/Cntr(USF)=0,0
Exp/Cntr=0.3,0.1

Type RM Length L Ch R = 1 ,1205    ,339,348.2,356.4
XS GIS Cut Line= 3
 2188925.5745677739625.1211749352188941.82725095739482.597644869
2188903.69595563739341.324321207
#Sta/Elev= 30
       0 1411.17      16 1410.46    28.1 1410.48    52.9 1409.65    72.4 1409.25
    96.6 1409.09   149.2 1409.22   165.6 1409.06   178.1 1408.51   190.5 1408.26
   194.9 1407.78   198.2 1407.04   201.4 1406.21   202.9 1406.06   204.7 1406.54
   205.91407.135   207.1 1407.57   211.2 1409.91   215.4 1410.78     221 1410.98
   227.8  1410.9   231.9 1410.68   237.3 1409.92   240.2 1409.81   248.5 1409.88
   252.6 1410.13   256.9 1410.76   269.2 1414.93   273.4 1416.52   289.8 1424.11
#Mann= 5 ,-1,0
       0     .07       0     100     .06       0   198.2    .045       0
   205.9     .06       0  253.45      .1       0
Bank Sta=198.2,205.9
XS Rating Curve= 0 ,0
Exp/Cntr(USF)=0,0
Exp/Cntr=0.3,0.1

Type RM Length L Ch R = 1 ,857     ,290.5,290.6,290.4
XS GIS Cut Line= 2
2188947.49376643739699.5769871082189439.82881109739191.534755814
#Sta/Elev= 30
       0 1415.54    35.5 1414.13    47.9 1412.87    70.2 1409.34    81.3 1409.84
      98 1409.78   203.9 1408.83     215 1408.53   276.3 1408.44   338.8 1407.87
   367.1 1406.91   376.5 1406.98   381.2 1405.97384.0744 1404.88   387.7 1403.72
   389.7 1403.85   393.2 1404.67   398.8 1406.65   406.7 1406.59   415.5 1406.97
   477.4 1407.33   485.9 1407.67   526.9  1408.2   548.1 1409.07     570 1411.23
   581.5  1411.9   630.2 1412.47     639 1412.29   666.2  1412.8   707.5 1414.76
#Mann= 6 ,-1,0
       0     .05       0     110     .07       0     240     .06       0
     380     .07       0384.0744    .045       0   393.2     .07       0
Bank Sta=384.0744,393.2
XS Rating Curve= 0 ,0
Exp/Cntr(USF)=0,0
Exp/Cntr=0.3,0.1

Type RM Length L Ch R = 1 ,566     ,65.6,65.6,65.7
XS GIS Cut Line= 2
2189211.18081274 739822.171602992189665.21020827739383.433352905
#Sta/Elev= 30
       0 1413.14    12.9 1411.54    26.9 1410.32    46.7 1409.11   101.5 1407.93
     146 1407.91   260.5 1407.36   301.3  1406.9   309.7 1406.43   318.2  1406.3
   321.1 1405.83  325.89 1404.41   329.6 1403.38   332.4 1403.86   334.31404.423
     338 1405.51     341 1406.09   346.8 1405.96   377.6 1406.33   463.1  1406.1
   482.3 1406.32   499.3 1406.79   518.7 1407.69   544.5 1410.27   582.8 1415.88
   598.3 1419.27   607.7 1420.92   611.6 1421.89   618.8 1423.86   631.4 1428.25
#Mann= 5 ,-1,0
       0     .05       0     150     .06       0     280     .07       0
  325.89    .045       0   334.3     .07       0
Bank Sta=325.89,334.3
XS Rating Curve= 0 ,0
Exp/Cntr(USF)=0,0
Exp/Cntr=0.3,0.1

Type RM Length L Ch R = 1 ,500     ,31.1,31,31
XS GIS Cut Line= 2
2189171.12074262739945.1962860182189708.86525022739435.754120917
#Sta/Elev= 30
       0 1442.73      18  1438.7    65.8  1425.3    95.1 1418.16   117.2 1413.76
   139.4 1410.87   177.8  1408.9   201.6 1408.22     299 1407.09   337.6 1406.84
   365.8 1406.96   442.2 1406.31     445 1405.68450.68621403.695   453.5 1403.22
456.28631403.698   464.3 1405.81   467.6 1406.05   481.8 1406.37   549.7  1405.8
     591 1406.13   623.2 1407.07     643 1408.42   651.6 1408.65   657.2  1409.4
   662.7 1410.81   679.8 1416.72   684.7 1418.12   728.8 1428.91   740.7 1432.45
#Mann= 6 ,-1,0
       0     .05       0     330     .07       0450.6862    .045       0
456.2863     .07       0     600     .06       0     610     .07       0
#XS Ineff= 2 , 0
          367.38 1407.49
Permanent Ineff=
       F       F
Bank Sta=450.6862,456.2863
XS Rating Curve= 0 ,0
Exp/Cntr(USF)=0,0
Exp/Cntr=0.3,0.1

Type RM Length L Ch R = 1 ,469     ,130.3,130.2,130.4
XS GIS Cut Line= 2
2189207.36351278739955.158565931 2189748.9199927739439.304622531
#Sta/Elev= 30
       0 1439.86     8.7 1437.44    31.9  1429.8    89.5 1414.85   101.5 1412.26
   112.3 1410.94   151.9 1408.86   182.7 1408.04   287.7 1406.61     421  1406.1
   426.4 1405.13430.27331402.988     432 1402.13437.49331402.988   443.3 1405.28
   446.2 1405.74   460.3 1406.24   524.8 1405.72   571.2 1405.94   619.8 1406.93
   632.9 1407.94   641.4 1409.19   646.6 1410.47   672.5 1419.59   697.2 1426.59
   708.2 1430.57   719.3 1435.97   724.8 1436.81   730.3 1437.01   747.9 1436.44
#Mann= 6 ,-1,0
       0     .05       0     280     .07       0430.2733    .045       0
437.4933     .07       0     550     .06       0     620     .07       0
Bank Sta=430.2733,437.4933
XS Rating Curve= 0 ,0
Exp/Cntr(USF)=0,0
Exp/Cntr=0.3,0.1

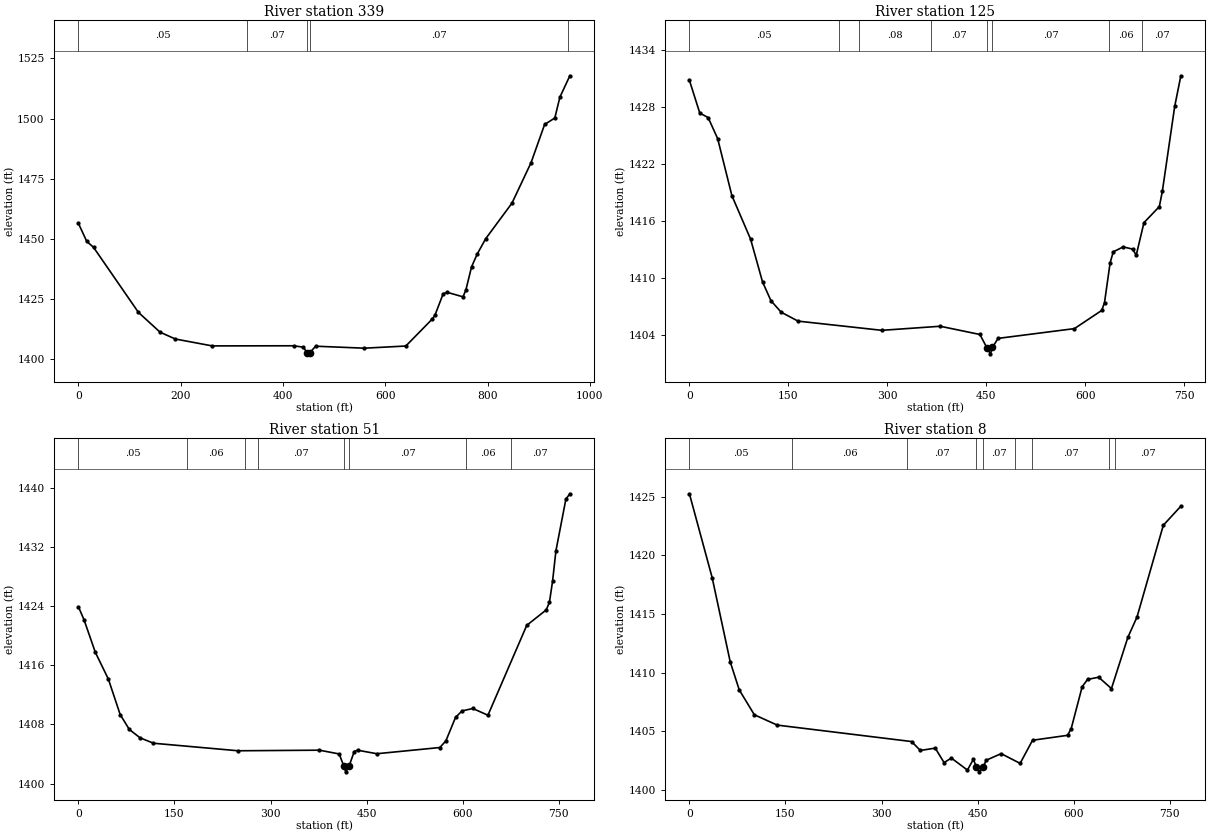
Type RM Length L Ch R = 1 ,339     ,213.8,214,214
XS GIS Cut Line= 3
2189273.53908076740072.4005784262189856.09563076739513.429313859
2189979.91837924739422.625964974
#Sta/Elev= 30
       0 1456.48    16.2 1449.02    29.6 1446.51   117.3  1419.5   159.7 1411.26
   189.5 1408.43   261.6 1405.57   420.6 1405.62   439.8 1405.04  446.711402.793
   449.5 1402.27   452.7 1402.79   463.8 1405.44   559.3 1404.62   640.2 1405.52
   692.2  1416.8   697.3 1418.42   713.2 1427.22   721.1 1427.84     752 1425.95
   757.6  1428.8   768.7 1438.42   779.7  1443.7   796.3  1450.1   847.7 1464.88
   884.9 1481.63   911.6  1497.6   931.5 1500.25   941.4 1508.92   960.9 1517.81
#Mann= 5 ,-1,0
       0     .05       0     330     .07       0  446.71    .045       0
   452.7     .07       0  957.35      .1       0
Bank Sta=446.71,452.7
XS Rating Curve= 0 ,0
Exp/Cntr(USF)=0,0
Exp/Cntr=0.3,0.1

Type RM Length L Ch R = 1 ,125     ,71.4,74.1,76.1
XS GIS Cut Line= 3
2189414.33972251740158.4912611782189561.37051402740080.325794556
2189981.30832676739682.787724421
#Sta/Elev= 30
       0 1430.84    15.7 1427.39    28.4 1426.91    42.8 1424.69    64.4 1418.67
    92.7 1414.09   110.8 1409.58   123.6 1407.59   139.1 1406.38   164.7 1405.44
   291.6 1404.47   380.1  1404.9   440.3 1404.03   451.11402.592   456.2 1401.99
   459.3 1402.67   467.8 1403.62   583.5 1404.65   624.9 1406.57   629.1 1407.39
   637.6 1411.59   642.4 1412.75   657.4 1413.27   671.6 1413.04   677.2  1412.4
   688.9 1415.83   712.2 1417.52   716.8 1419.15   735.5 1428.09   744.8 1431.32
#Mann= 8 ,-1,0
       0     .05       0  226.52     .06       0  256.52     .08       0
  366.52     .07       0   451.1    .045       0   459.3     .07       0
  636.52     .06       0  686.52     .07       0
Bank Sta=451.1,459.3
XS Rating Curve= 0 ,0
Exp/Cntr(USF)=0,0
Exp/Cntr=0.3,0.1

Type RM Length L Ch R = 1 ,51      ,43,43,43
XS GIS Cut Line= 4
2189464.88583478740154.3067585192189769.24858386739963.587771573
2189905.39606127739887.6377325242190059.54651089739687.917259469
#Sta/Elev= 30
       0 1423.91     8.6  1422.2    26.4 1417.76    46.7 1414.15    65.2 1409.34
    79.4 1407.33    96.1  1406.2   117.2 1405.46   249.3 1404.44   376.3 1404.52
   407.2 1404.01   414.41402.377   417.5 1401.59   422.7 1402.38   430.7 1404.34
   435.8 1404.52     466 1404.04   564.4 1404.88   573.8 1405.78   588.9 1408.96
     599 1409.83   615.8 1410.16   639.5 1409.25   700.1 1421.41   730.4 1423.49
   735.5 1424.52   740.5 1427.43   745.6 1431.47   761.2 1438.48   767.4 1439.21
#Mann= 8 ,-1,0
       0     .05       0     170     .06       0     260     .08       0
     280     .07       0   414.4    .045       0   422.7     .07       0
  605.08     .06       0  675.08     .07       0
Bank Sta=414.4,422.7
XS Rating Curve= 0 ,0
Exp/Cntr(USF)=0,0
Exp/Cntr=0.3,0.1

Type RM Length L Ch R = 1 ,8       ,,,
XS GIS Cut Line= 4
2189470.23046716740196.2199282162189774.59321624740005.500941271
2189910.74069364739929.5509022212190064.89114327739729.830429166
#Sta/Elev= 30
       0 1425.24    35.5  1418.1    63.7 1410.93    77.8 1408.54   101.4 1406.42
   137.1 1405.54   346.9 1404.14   360.6 1403.38   383.9 1403.58   397.6 1402.35
   409.1 1402.73   434.1 1401.71   443.4 1402.63     448 1401.97   452.6 1401.56
   458.4 1401.95   463.5 1402.55   486.8 1403.11   516.4 1402.28   535.8 1404.25
   590.5 1404.67   596.2 1405.25   613.3 1408.81   621.7 1409.43     639 1409.62
     659 1408.65   684.6 1413.01   698.9 1414.74     740 1422.56767.3701 1424.18
#Mann= 9 ,-1,0
       0     .05       0     160     .06       0     340     .07       0
     448    .045       0   458.4     .07       0  509.18     .06       0
  535.08     .07       0  655.08     .06       0  665.08     .07       0
Bank Sta=448,458.4
XS Rating Curve= 0 ,0
Exp/Cntr(USF)=0,0
Exp/Cntr=0.3,0.1
LCMann Table=0

Chan Stop Cuts=-1
Use User Specified Reach Order=0
Composite Channel Slope=5